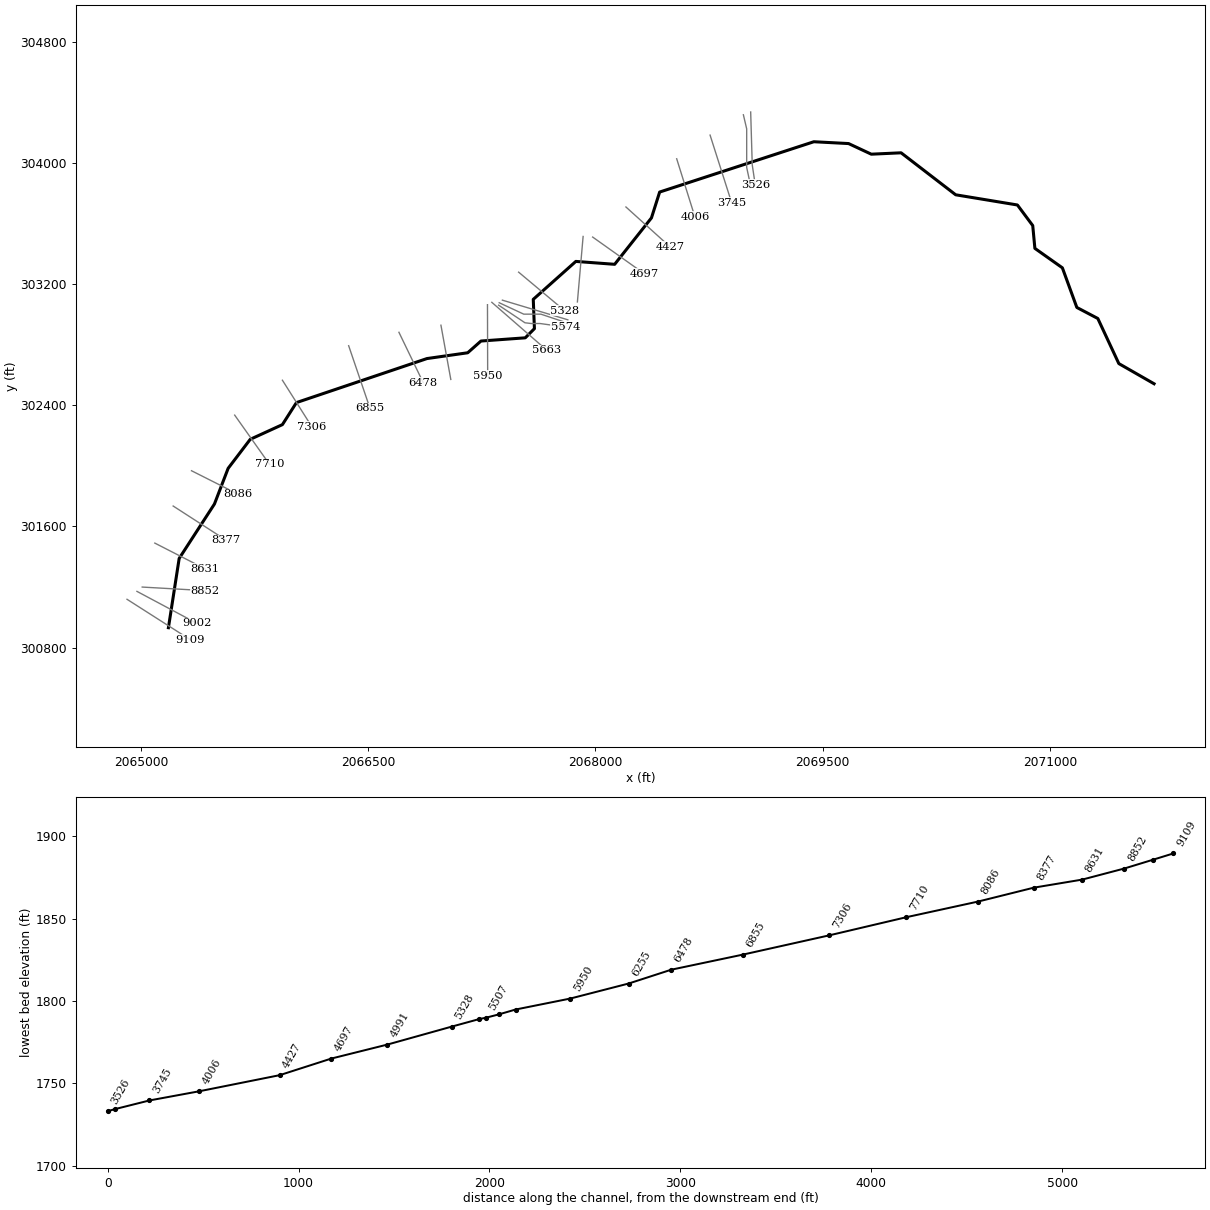
--- KTCHNCKT1.prj (project) ---

Proj Title=KTCHNCKT1
Current Plan=p01
Default Exp/Contr=0.3,0.1
English Units
Geom File=g01
Flow File=f01
Plan File=p01
Y Axis Title=Elevation
X Axis Title(PF)=Main Channel Distance
X Axis Title(XS)=Station
BEGIN DESCRIPTION:
Stream Name- Kitchen Creek Tributary 1
Flood Zone: Zone A
Greenbrier County, WV
County-Wide Study
WVDHSEM-2018-3, Flood Risk Project
HEC-RAS Version: 5.0.7
General Notes:
For the Hydrology Regression was used.
END DESCRIPTION:
DSS Export Rating Curves= 0
DSS Export Rating Curve Sorted= 0
DSS Export Volume Flow Curves= 0
DXF Filename=..\J2.
DXF OffsetX= 0
DXF OffsetY= 0
DXF ScaleX= 1
DXF ScaleY= 10

--- KTCHNCKT1.p01 (plan) ---

Plan Title=Floodplain
Program Version=5.07
Short Identifier=Floodplain
Geom File=g01
Flow File=f01
Subcritical Flow
K Sum by GR= 0
Std Step Tol= 0.01
Critical Tol= 0.01
Num of Std Step Trials= 20
Max Error Tol= 0.3
Flow Tol Ratio= 0.001
Split Flow NTrial= 30
Split Flow Tol= 0.02
Split Flow Ratio= 0.02
Log Output Level= 0
Friction Slope Method= 1
Unsteady Friction Slope Method= 2
Unsteady Bridges Friction Slope Method= 1
Parabolic Critical Depth
Global Vel Dist= 0 , 0 , 0
Global Log Level= 0
CheckData=True
Encroach Param=-1 ,0,0, 0
Computation Interval=1MIN
Output Interval=1HOUR
Instantaneous Interval=1HOUR
Mapping Interval=1HOUR
Computation Time Step Use Courant=        0
Computation Time Step Use Time Series=    0
Computation Time Step Count To Double=0
Computation Time Step Max Doubling=0
Computation Time Step Max Halving=0
Computation Time Step Residence Courant=0
Run HTab= 0
Run UNet= 0
Run Sediment= 0
Run PostProcess= 0
Run WQNet= 0
Run RASMapper= 0
UNET Theta= 1
UNET Theta Warmup= 1
UNET ZTol= 0.02
UNET ZSATol= 0.02
UNET MxIter= 20
UNET Max Iter WO Improvement= 0
UNET MaxInSteps= 0
UNET DtIC= 0
UNET DtMin= 0
UNET MaxCRTS= 20
UNET WFStab= 2
UNET SFStab= 1
UNET WFX= 1
UNET SFX= 1
UNET 1D Methodology=Finite Difference
UNET DSS MLevel= 4
UNET Pardiso=0
UNET DZMax Abort= 100
UNET Use Existing IB Tables=-1
UNET Froude Reduction=False
UNET Froude Limit= 0.8
UNET Froude Power= 4
UNET D1 Cores= 0
UNET D2 Coriolis=0
UNET D2 Cores= 0
UNET D2 Theta= 1
UNET D2 Theta Warmup= 1
UNET D2 Z Tol= 0.01
UNET D2 Volume Tol= 0.01
UNET D2 Max Iterations= 20
UNET D2 Equation= 0
UNET D2 RampUpFraction=0.1
UNET D2 TimeSlices= 1
UNET D2 BCVolumeCheck=0
UNET D1D2 MaxIter= 0
UNET D1D2 ZTol=0.01
UNET D1D2 QTol=0.1
UNET D1D2 MinQTol=1
Write IC File= 0
Write IC File at Fixed DateTime=0
Write IC File at Sim End=0
Echo Input=False
Echo Parameters=False
Echo Output=False
Write Detailed= 0
HDF Write Warmup=0
HDF Write Time Slices=0
HDF Flush=0
HDF Face Node Velocities=0
HDF Compression= 1
HDF Chunk Size= 1
HDF Spatial Parts= 1
HDF Use Max Rows=0
HDF Fixed Rows= 1
Calibration Method= 0
Calibration Iterations= 20
Calibration Max Change=0.05
Calibration Tolerance=0.2
Calibration Maximum=1.5
Calibration Minimum=0.5
Calibration Optimization Method= 1
WQ AD Non Conservative
WQ ULTIMATE=-1
WQ Max Comp Step=1HOUR
WQ Output Interval=15MIN
WQ Output Selected Increments= 0
WQ Output face flow=0
WQ Output face velocity=0
WQ Output face area=0
WQ Output face dispersion=0
WQ Output cell volume=0
WQ Output cell surface area=0
WQ Output cell continuity=0
WQ Output cumulative cell continuity=0
WQ Output face conc=0
WQ Output face dconc_dx=0
WQ Output face courant=0
WQ Output face peclet=0
WQ Output face adv mass=0
WQ Output face disp mass=0
WQ Output cell mass=0
WQ Output cell source sink temp=0
WQ Output nsm pathways=0
WQ Output nsm derived pathways=0
WQ Output MaxMinRange=-1
WQ Daily Max Min Mean=-1
WQ Daily Range=0
WQ Daily Time=0
WQ Create Restart=0
WQ Fixed Restart=0
WQ System Summary=0
WQ Write To DSS=0
WQ Use Fixed Temperature=0
Sorting and Armoring Iterations= 10
XS Update Threshold= 0.02
Bed Roughness Predictor= 0
Hydraulics Update Threshold= 0.02
Energy Slope Method= 1
Volume Change Method= 1
Sediment Retention Method= 0
XS Weighting Method= 0
Number of US Weighted Cross Sections= 1
Number of DS Weighted Cross Sections= 1
Upstream XS Weight=0
Main XS Weight=1
Downstream XS Weight=0
Number of DS XS's Weighted with US Boundary= 1
Upstream Boundary Weight= 1
Weight of XSs Associated with US Boundary= 0
Number of US XS's Weighted with DS Boundary= 1
Downstream Boundary Weight= 0.5
Weight of XSs Associated with DS Boundary= 0.5
Percentile Method= 0
Sediment Output Level= 3
Mass or Volume Output= 0
Output Increment Type= 1
Profile and TS Output Increment= 1
XS Output Flag= 0
XS Output Increment= 10
Write Gradation File= 0
Read Gradation Hotstart= 0
Write HDF5 File= 1
Write Binary Output= 1
Write DSS Sediment File= 0
SV Curve= 0
Specific Gage Flag= 0

--- KTCHNCKT1.f01 (steady flow) ---

Flow Title=Flow
Program Version=5.07
Number of Profiles= 6
Profile Names=f1p,f10p,f4p,f2p,f02p,f1pplus
River Rch & RM=KTCHNCKT1,Main            ,9109
     634     336     447     537     884     938
River Rch & RM=KTCHNCKT1,Main            ,6855
     715     381     504     606     994    1060
River Rch & RM=KTCHNCKT1,Main            ,2499
     856     459     606     727    1190    1270
Boundary for River Rch & Prof#=ALUMRN,Main            , 1
Up Type= 0
Dn Type= 3
Dn Slope=0.008838
Boundary for River Rch & Prof#=ALUMRN,Main            , 2
Up Type= 0
Dn Type= 3
Dn Slope=0.008838
Boundary for River Rch & Prof#=ALUMRN,Main            , 3
Up Type= 0
Dn Type= 3
Dn Slope=0.008838
Boundary for River Rch & Prof#=ALUMRN,Main            , 4
Up Type= 0
Dn Type= 3
Dn Slope=0.008838
Boundary for River Rch & Prof#=ALUMRN,Main            , 5
Up Type= 0
Dn Type= 3
Dn Slope=0.008838
Boundary for River Rch & Prof#=ALUMRN,Main            , 6
Up Type= 0
Dn Type= 3
Dn Slope=0.008838
Boundary for River Rch & Prof#=KTCHNCK,Main            , 1
Up Type= 0
Dn Type= 3
Dn Slope=0.005801
Boundary for River Rch & Prof#=KTCHNCK,Main            , 2
Up Type= 0
Dn Type= 3
Dn Slope=0.005801
Boundary for River Rch & Prof#=KTCHNCK,Main            , 3
Up Type= 0
Dn Type= 3
Dn Slope=0.005801
Boundary for River Rch & Prof#=KTCHNCK,Main            , 4
Up Type= 0
Dn Type= 3
Dn Slope=0.005801
Boundary for River Rch & Prof#=KTCHNCK,Main            , 5
Up Type= 0
Dn Type= 3
Dn Slope=0.005801
Boundary for River Rch & Prof#=KTCHNCK,Main            , 6
Up Type= 0
Dn Type= 3
Dn Slope=0.005801
Boundary for River Rch & Prof#=KTCHNCKT1,Main            , 1
Up Type= 0
Dn Type= 3
Dn Slope=0.024951
Boundary for River Rch & Prof#=KTCHNCKT1,Main            , 2
Up Type= 0
Dn Type= 3
Dn Slope=0.024951
Boundary for River Rch & Prof#=KTCHNCKT1,Main            , 3
Up Type= 0
Dn Type= 3
Dn Slope=0.024951
Boundary for River Rch & Prof#=KTCHNCKT1,Main            , 4
Up Type= 0
Dn Type= 3
Dn Slope=0.024951
Boundary for River Rch & Prof#=KTCHNCKT1,Main            , 5
Up Type= 0
Dn Type= 3
Dn Slope=0.024951
Boundary for River Rch & Prof#=KTCHNCKT1,Main            , 6
Up Type= 0
Dn Type= 3
Dn Slope=0.024951
Boundary for River Rch & Prof#=MILLCK1,Main            , 1
Up Type= 0
Dn Type= 3
Dn Slope=0.000839
Boundary for River Rch & Prof#=MILLCK1,Main            , 2
Up Type= 0
Dn Type= 3
Dn Slope=0.000839
Boundary for River Rch & Prof#=MILLCK1,Main            , 3
Up Type= 0
Dn Type= 3
Dn Slope=0.000839
Boundary for River Rch & Prof#=MILLCK1,Main            , 4
Up Type= 0
Dn Type= 3
Dn Slope=0.000839
Boundary for River Rch & Prof#=MILLCK1,Main            , 5
Up Type= 0
Dn Type= 3
Dn Slope=0.000839
Boundary for River Rch & Prof#=MILLCK1,Main            , 6
Up Type= 0
Dn Type= 3
Dn Slope=0.000839
Boundary for River Rch & Prof#=MILLCK1T1,Main            , 1
Up Type= 0
Dn Type= 3
Dn Slope=0.000001
Boundary for River Rch & Prof#=MILLCK1T1,Main            , 2
Up Type= 0
Dn Type= 3
Dn Slope=0.000001
Boundary for River Rch & Prof#=MILLCK1T1,Main            , 3
Up Type= 0
Dn Type= 3
Dn Slope=0.000001
Boundary for River Rch & Prof#=MILLCK1T1,Main            , 4
Up Type= 0
Dn Type= 3
Dn Slope=0.000001
Boundary for River Rch & Prof#=MILLCK1T1,Main            , 5
Up Type= 0
Dn Type= 3
Dn Slope=0.000001
Boundary for River Rch & Prof#=MILLCK1T1,Main            , 6
Up Type= 0
Dn Type= 3
Dn Slope=0.000001
Boundary for River Rch & Prof#=RENICKCK,Main            , 1
Up Type= 0
Dn Type= 3
Dn Slope=0.003087
Boundary for River Rch & Prof#=RENICKCK,Main            , 2
Up Type= 0
Dn Type= 3
Dn Slope=0.003087
Boundary for River Rch & Prof#=RENICKCK,Main            , 3
Up Type= 0
Dn Type= 3
Dn Slope=0.003087
Boundary for River Rch & Prof#=RENICKCK,Main            , 4
Up Type= 0
Dn Type= 3
Dn Slope=0.003087
Boundary for River Rch & Prof#=RENICKCK,Main            , 5
Up Type= 0
Dn Type= 3
Dn Slope=0.003087
Boundary for River Rch & Prof#=RENICKCK,Main            , 6
Up Type= 0
Dn Type= 3
Dn Slope=0.003087
Boundary for River Rch & Prof#=SNAKERN,Main            , 1
Up Type= 0
Dn Type= 3
Dn Slope=0.008894
Boundary for River Rch & Prof#=SNAKERN,Main            , 2
Up Type= 0
Dn Type= 3
Dn Slope=0.008894
Boundary for River Rch & Prof#=SNAKERN,Main            , 3
Up Type= 0
Dn Type= 3
Dn Slope=0.008894
Boundary for River Rch & Prof#=SNAKERN,Main            , 4
Up Type= 0
Dn Type= 3
Dn Slope=0.008894
Boundary for River Rch & Prof#=SNAKERN,Main            , 5
Up Type= 0
Dn Type= 3
Dn Slope=0.008894
Boundary for River Rch & Prof#=SNAKERN,Main            , 6
Up Type= 0
Dn Type= 3
Dn Slope=0.008894
DSS Import GetInterval= 0
DSS Import GetPeak= 0
DSS Import FillOption= 0

--- KTCHNCKT1.g01 (geometry) ---

Geom Title=Geometry
Program Version=5.07

River Reach=KTCHNCKT1       ,Main
Reach XY= 30
2065179.88442102300931.2777345482065250.88395095301388.633119047
2065483.75684476 301748.045129882065574.31998387301983.682125792
2065720.06509918302175.216847718 2065932.5210391302272.316062957
2066025.29513177302417.8331603712066887.18415603302708.555019885
2067156.22594076302746.8210194562067243.75594944 302824.32611379
2067536.45811993302845.505861461 2067596.6909391302906.114007965
 2067589.0849832303099.4791067992067870.16808245303350.057017714
2068126.47301602303330.9120428712068369.51714936303637.527899459
2068423.65483636303808.0698812162069441.91100195304140.300844043
2069671.08114728 304128.273965212069821.13301253304058.083160713
2070017.99088651 304067.238982292070378.47310519303789.943277046
2070786.02511162303722.6688053012070887.22733703303586.721898705
2070901.40020895303436.1513337052071082.90017402303307.738204718
2071178.38620353303046.0195680412071316.92792118302973.160789877
2071455.73013702 302675.359876292071688.36943552302542.134420961

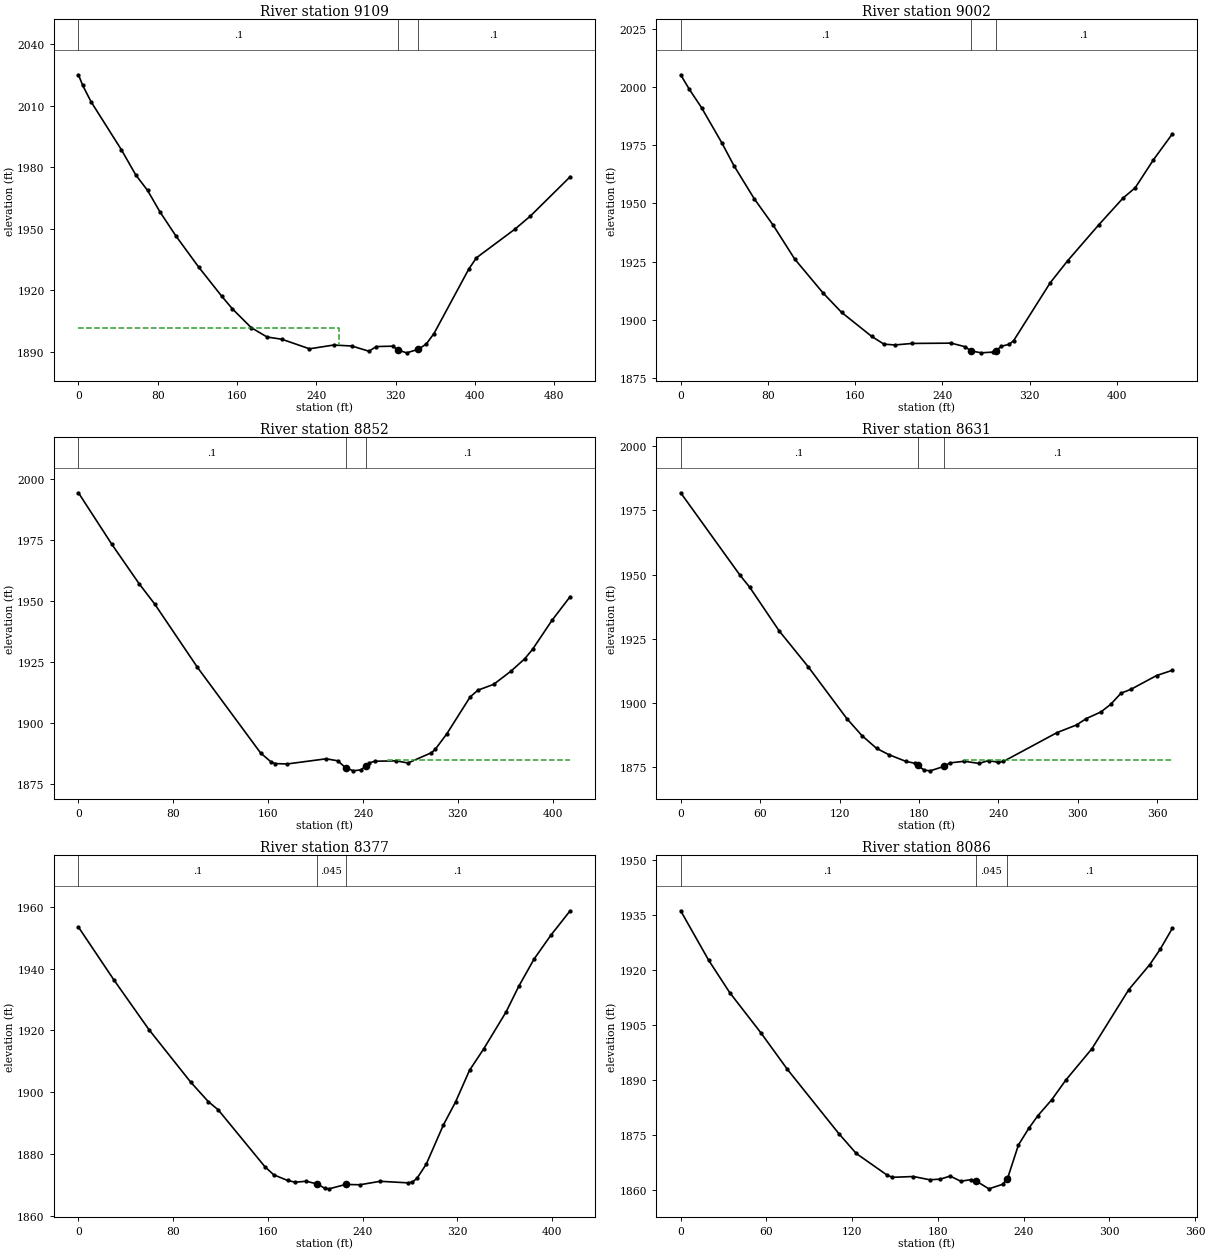
Type RM Length L Ch R = 1 ,9109    ,105.9,106.9,107.1
XS GIS Cut Line= 2
2064906.50701502301118.9509156352065324.47566727300852.023956046
#Sta/Elev= 30
       0 2025.01     4.3 2019.84    12.7  2011.9    43.3 1988.51    57.8 1976.24
    69.7  1968.7    82.2 1958.24    98.2 1946.58   121.1 1931.45   144.5 1917.16
   155.2 1911.04   174.2 1901.86   190.3 1897.27   205.1  1896.2     233 1891.53
   257.4 1893.37   275.7  1892.9     293 1890.35   300.4 1892.63   316.8 1892.81
  322.761890.872     331 1889.57  342.921891.314   350.8 1893.89   358.6 1898.98
   393.6 1930.31   401.4 1935.87   440.3 1949.85   455.9 1956.24   495.9 1975.33
#Mann= 3 ,-1 , 0
       0      .1       0  322.76    .045       0  342.92      .1       0
#XS Ineff= 2 , 0
          262.59 1901.51
Permanent Ineff=
       F       F
Bank Sta=322.76,342.92
XS Rating Curve= 0 ,0
Exp/Cntr=0.3,0.1

Type RM Length L Ch R = 1 ,9002    ,144.9,150.3,154.4
XS GIS Cut Line= 2
2064972.04697046301171.2001999992065369.96962042300959.126810621
#Sta/Elev= 30
       0 2005.28       8 1998.98    19.1 1991.17    37.7 1976.05    48.8 1966.23
    67.4 1952.02    84.8 1940.63   104.6 1926.04   130.6 1911.46   147.5 1903.16
   175.2 1892.79   186.4 1889.47   196.4 1889.13   212.4 1889.78   248.1 1889.91
   260.8 1888.37   266.1 1886.59   275.6 1885.74   286.8 1886.08   289.3  1886.7
   294.1 1888.56   301.4 1889.44   305.4 1891.03   338.8 1915.81   354.8  1925.3
   383.4 1940.78   405.6 1952.24   416.9 1956.76   433.5 1968.72   450.9 1979.88
#Mann= 3 ,-1 , 0
       0      .1       0   266.1    .045       0   289.3      .1       0
Bank Sta=266.1,289.3
XS Rating Curve= 0 ,0
Exp/Cntr(USF)=0,0
Exp/Cntr=0.3,0.1

Type RM Length L Ch R = 1 ,8852    ,225,220.9,216.6
XS GIS Cut Line= 2
2065006.76731318301199.6800848842065420.82980528301176.242795795
#Sta/Elev= 30
       0 1994.26    28.1 1973.21    51.1 1957.08    64.3 1948.72   100.4 1922.76
   153.6 1887.75   162.8 1883.91   166.1 1883.38     176 1883.22   208.9 1885.34
   218.7 1884.52  225.321881.666   231.9 1880.41   238.4 1880.84  242.391882.415
     245 1883.61     250 1884.34     268  1884.5   277.9 1883.62   297.6  1887.8
   300.9 1889.19   310.7 1895.57   330.4  1910.7     337 1913.45   350.2 1915.82
   364.8 1921.23   376.4 1926.29     383 1930.16   399.4 1942.04   414.7 1951.73
#Mann= 3 ,-1 , 0
       0      .1       0  225.32    .045       0  242.39      .1       0
#XS Ineff= 2 , 0
                          261.46         1884.82
Permanent Ineff=
       F       F
Bank Sta=225.32,242.39
XS Rating Curve= 0 ,0
Exp/Cntr=0.3,0.1

Type RM Length L Ch R = 1 ,8631    ,254.3,253.4,252.2
XS GIS Cut Line= 2
2065090.10080794301490.0446616262065420.82980528 301320.77400279
#Sta/Elev= 30
       0 1981.87    44.8 1949.81    52.2 1945.08    74.3  1928.2    96.3  1914.2
   125.5 1894.02   136.9 1887.41     148 1882.42   157.2 1879.98   170.1 1877.36
   176.7 1876.64  179.051875.767     184 1873.95   188.5 1873.67  199.051875.421
   203.5 1876.77   214.3 1877.39   225.4 1876.56   232.8 1877.68   240.1 1876.94
   243.8 1877.31   284.4 1888.56   299.1 1891.53   306.5 1894.01   317.5 1896.59
   324.9 1899.55   332.7 1903.89   340.1 1905.37   359.6 1910.76   371.5 1912.79
#Mann= 3 ,-1 , 0
       0      .1       0  179.05    .045       0  199.05      .1       0
#XS Ineff= 2 , 0
                          214.42         1877.97
Permanent Ineff=
       F       F
Bank Sta=179.05,199.05
XS Rating Curve= 0 ,0
Exp/Cntr=0.3,0.1

Type RM Length L Ch R = 1 ,8377    ,289.9,291.3,292.2
XS GIS Cut Line= 2
2065211.19439778301734.8364948782065560.15268937301509.576118633
#Sta/Elev= 30
       0 1953.45    29.9 1936.39    59.5 1920.31    94.7 1903.35   109.6 1897.03
   118.1 1894.32   157.5 1875.93     165 1873.31   176.7 1871.48   183.2 1870.92
   192.3 1871.24   201.8 1870.35   207.9 1868.99   211.8 1868.78  225.661870.204
   237.8  1870.1   254.8 1871.22   278.2 1870.72   282.1 1870.97     286 1872.21
   293.8 1876.78   308.2 1889.41   318.5 1896.87   330.3 1907.11   342.2 1913.99
   361.2    1926   371.9 1934.29   384.9 1943.15   399.1 1950.85   415.3 1958.72
#Mann= 3 ,-1 , 0
       0      .1       0   201.8    .045       0  225.66      .1       0
Bank Sta=201.8,225.66
XS Rating Curve= 0 ,0
Exp/Cntr=0.3,0.1

Type RM Length L Ch R = 1 ,8086    ,380,376.4,368.5
XS GIS Cut Line= 2
2065332.28831568301967.9095195382065639.57969585301812.961338624
#Sta/Elev= 30
       0 1936.21    19.6 1922.71    34.3  1913.9    56.4 1902.78    74.7 1892.94
   110.7 1875.41   122.9    1870   144.5 1864.09   148.2  1863.5   162.9 1863.72
   174.2 1862.84   181.6    1863   188.6 1863.84     196 1862.44   203.3 1862.88
   206.41862.576   215.7 1860.36   225.4 1861.61  228.231862.948     229 1863.51
   236.4 1872.36   243.7 1876.91   249.9 1880.28   259.7 1884.68   269.5 1890.02
   287.8 1898.59   313.6 1914.71   328.3 1921.54   335.6 1925.74   344.1 1931.45
#Mann= 3 ,-1 , 0
       0      .1       0   206.4    .045       0  228.23      .1       0
Bank Sta=206.4,228.23
XS Rating Curve= 0 ,0
Exp/Cntr=0.3,0.1

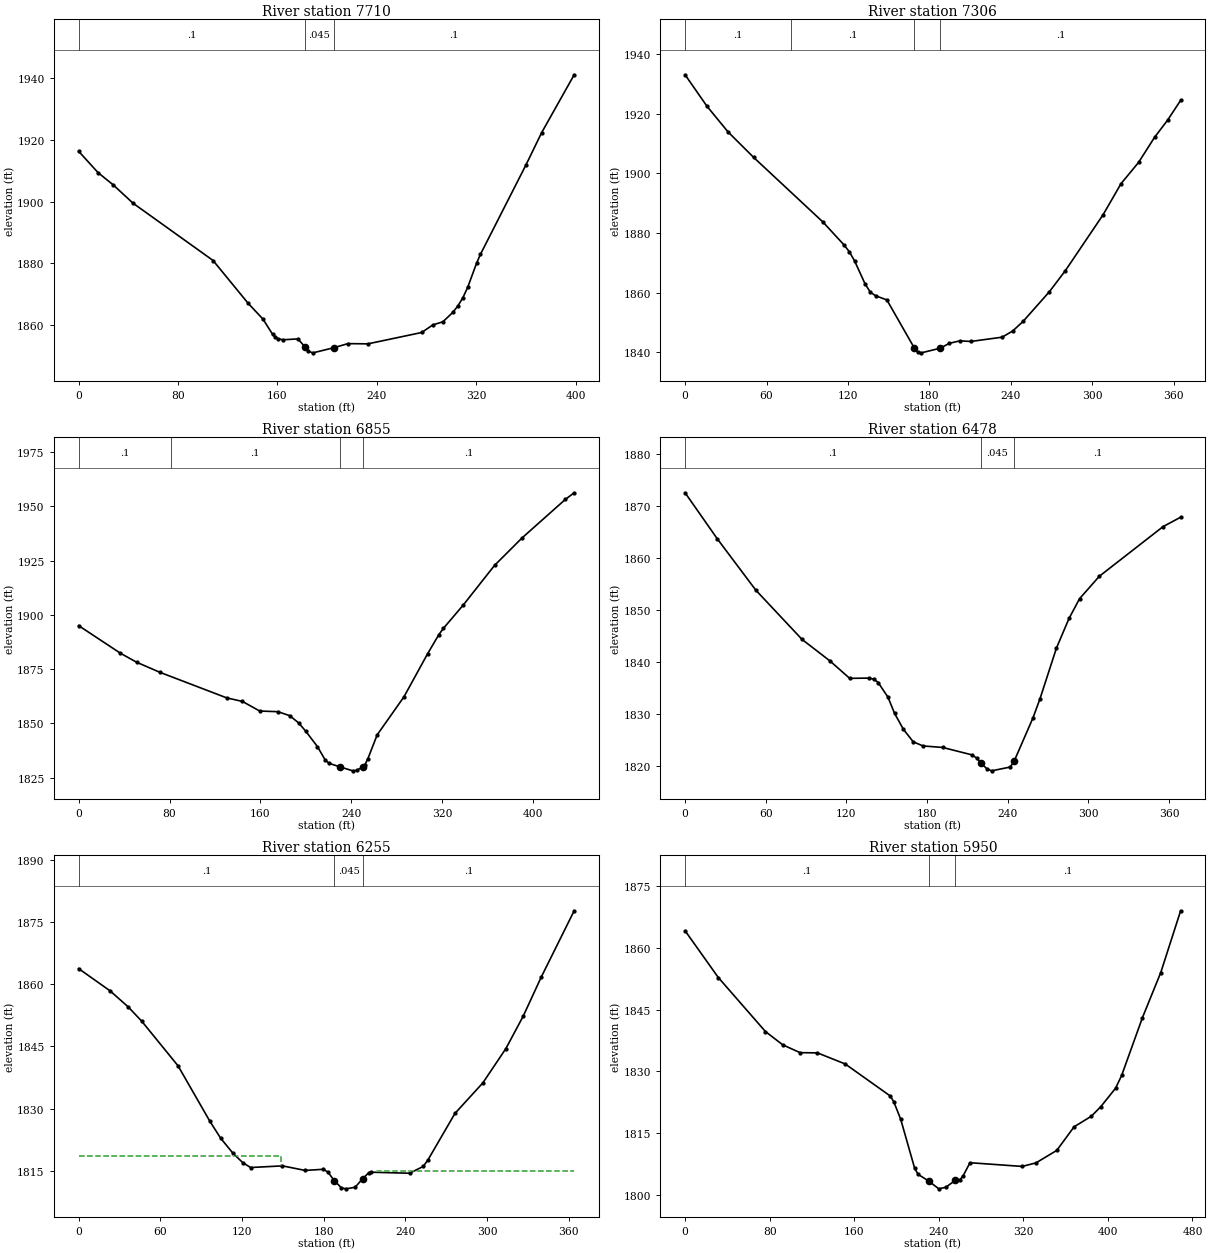
Type RM Length L Ch R = 1 ,7710    ,402.7,403.1,400.4
XS GIS Cut Line= 2
2065617.44456953 302335.096777292065847.91326869302009.576102883
#Sta/Elev= 30
       0 1916.34    15.7 1909.37    27.8 1905.43    43.8 1899.46   108.2 1880.85
   136.3    1867   148.4 1861.79   156.1 1856.86   158.1 1856.09   160.4 1855.45
   164.4 1855.09   176.5 1855.38     182 1852.85   184.5 1851.37   188.6 1850.85
   205.5 1852.53   216.7 1853.84   232.8 1853.77   276.1 1857.46     285 1859.91
   293.1 1860.93   301.1 1863.97   305.1 1866.03   309.2 1868.72   313.2 1872.23
   320.3 1880.02   323.3  1882.8   360.1 1911.98   372.6 1922.37   398.8 1941.19
#Mann= 3 , 0 , 0
       0      .1       0     182    .045       0   205.5      .1       0
Bank Sta=182,205.5
XS Rating Curve= 0 ,0
Exp/Cntr=0.3,0.1

Type RM Length L Ch R = 1 ,7306    ,452.7,451.8,447.8
XS GIS Cut Line= 2
2065932.54859811302565.5658045412066127.86119962302256.971933544
#Sta/Elev= 30
       0 1933.01    16.1 1922.48    31.7 1913.85    50.5 1905.34   101.6 1883.68
   117.1 1876.02     121 1873.76   124.9 1870.66   132.6    1863   136.5 1860.18
   140.4 1858.98   148.7 1857.59  168.961841.461   171.4 1840.08   174.1 1839.86
     188 1841.41   194.7 1843.04   202.5 1843.89   210.5 1843.67   233.6  1845.1
   241.4 1847.17   249.1 1850.39   268.5 1860.35   280.2 1867.37     308 1886.09
   321.3 1896.56   334.2 1903.65     346 1912.07   355.6 1917.82   365.2 1924.44
#Mann= 4 ,-1 , 0
       0      .1       0   78.23      .1       0  168.96    .045       0
     188      .1       0
Bank Sta=168.96,188
XS Rating Curve= 0 ,0
Exp/Cntr=0.3,0.1

Type RM Length L Ch R = 1 ,6855    ,374.7,376.5,377.9
XS GIS Cut Line= 2
2066370.04870737 302793.430178212066510.67342612302380.669848874
#Sta/Elev= 30
       0 1895.08    36.8 1882.36    51.1  1878.2    71.4  1873.6   130.3  1861.8
   144.2 1860.15   159.3 1855.74   175.4 1855.43   185.8 1853.59   193.6 1850.28
   199.7 1846.55   210.1 1839.39     217 1833.18   220.5 1831.63  229.991830.002
   241.3 1828.18   244.7 1828.37     2501830.037   251.7 1830.72   254.6 1833.82
   262.7 1844.73   286.3 1862.28   307.1 1882.11     317 1890.93     321 1893.82
   338.3 1904.45     366 1922.82   390.3 1935.52   428.4 1953.27   436.1 1956.29
#Mann= 4 ,-1 , 0
       0      .1       0   80.93      .1       0  229.99    .045       0
     250      .1       0
Bank Sta=229.99,250
XS Rating Curve= 0 ,0
Exp/Cntr=0.3,0.1

Type RM Length L Ch R = 1 ,6478    ,225.2,222.9,218.6
XS GIS Cut Line= 2
2066702.07986745302881.9719958752066862.23604319 302549.94050771
#Sta/Elev= 30
       0  1872.5      24 1863.62    52.6 1853.76      87 1844.28   107.8 1840.13
   122.4 1836.79   136.9 1836.84   140.6  1836.6   143.6 1835.99   150.9 1833.17
   155.8 1830.05   162.4 1826.98   169.7 1824.57     177 1823.78   191.6 1823.49
   213.4 1822.06   217.1 1821.41  219.831820.534   224.6 1819.36     228 1818.99
   241.8 1819.72  244.671820.806   258.8  1829.2     264 1832.87   276.2  1842.6
   285.6 1848.33   293.4 1852.11   308.1 1856.43   355.5 1865.98   368.6  1867.8
#Mann= 3 ,-1 , 0
       0      .1       0  219.83    .045       0  244.67      .1       0
Bank Sta=219.83,244.67
XS Rating Curve= 0 ,0
Exp/Cntr=0.3,0.1

Type RM Length L Ch R = 1 ,6255    ,307.2,305.6,301.4
XS GIS Cut Line= 2
2066979.42347285302928.8469021322067044.52767336302570.774127468
#Sta/Elev= 30
       0 1863.82      23 1858.47    36.3  1854.6    46.3 1851.13      73 1840.33
    96.4 1826.92   104.3 1822.84   113.3 1819.22   120.6 1816.92   126.3 1815.76
   149.7 1816.16   166.3 1815.06   179.7 1815.33     183 1814.67   187.8 1812.58
     193 1810.84   196.4 1810.61     203 1810.99  208.651813.076     213 1814.49
   214.9 1814.63     243 1814.38     253 1816.01   256.4 1817.53   276.4 1828.85
   296.8 1836.19   313.7 1844.47   326.4 1852.28   339.7 1861.76   363.9 1877.79
#Mann= 3 , 0 , 0
       0      .1       0   187.8    .045       0  208.65      .1       0
#XS Ineff= 2 , 0
           148.5 1818.44  219.35         1815.01
Permanent Ineff=
       F       F
Bank Sta=187.8,208.65
XS Rating Curve= 0 ,0
Exp/Cntr=0.3,0.1

Type RM Length L Ch R = 1 ,5950    ,274.9,286.9,294.4
XS GIS Cut Line= 2
2067286.71518111303064.2636260392067288.01734385302595.513579294
#Sta/Elev= 30
       0 1864.11    31.4 1852.77      76 1839.66    92.4 1836.43   108.8 1834.53
   125.2 1834.48   151.4  1831.8   194.1 1824.02   197.4 1822.63   203.9 1818.43
   217.1 1806.54   220.3 1805.03  230.531803.368     240 1801.49   246.6 1801.87
  255.681803.552   259.7 1803.63     263 1804.62   269.5 1807.83   318.8 1806.93
   331.9 1807.78   351.6 1810.81     368 1816.54   384.4 1819.12   393.3 1821.44
   407.3 1825.92     413 1829.01   432.7 1843.05     450 1853.98   468.8 1868.96
#Mann= 3 ,-1 , 0
       0      .1       0  230.53    .045       0  255.68      .1       0
Bank Sta=230.53,255.68
XS Rating Curve= 0 ,0
Exp/Cntr=0.3,0.1

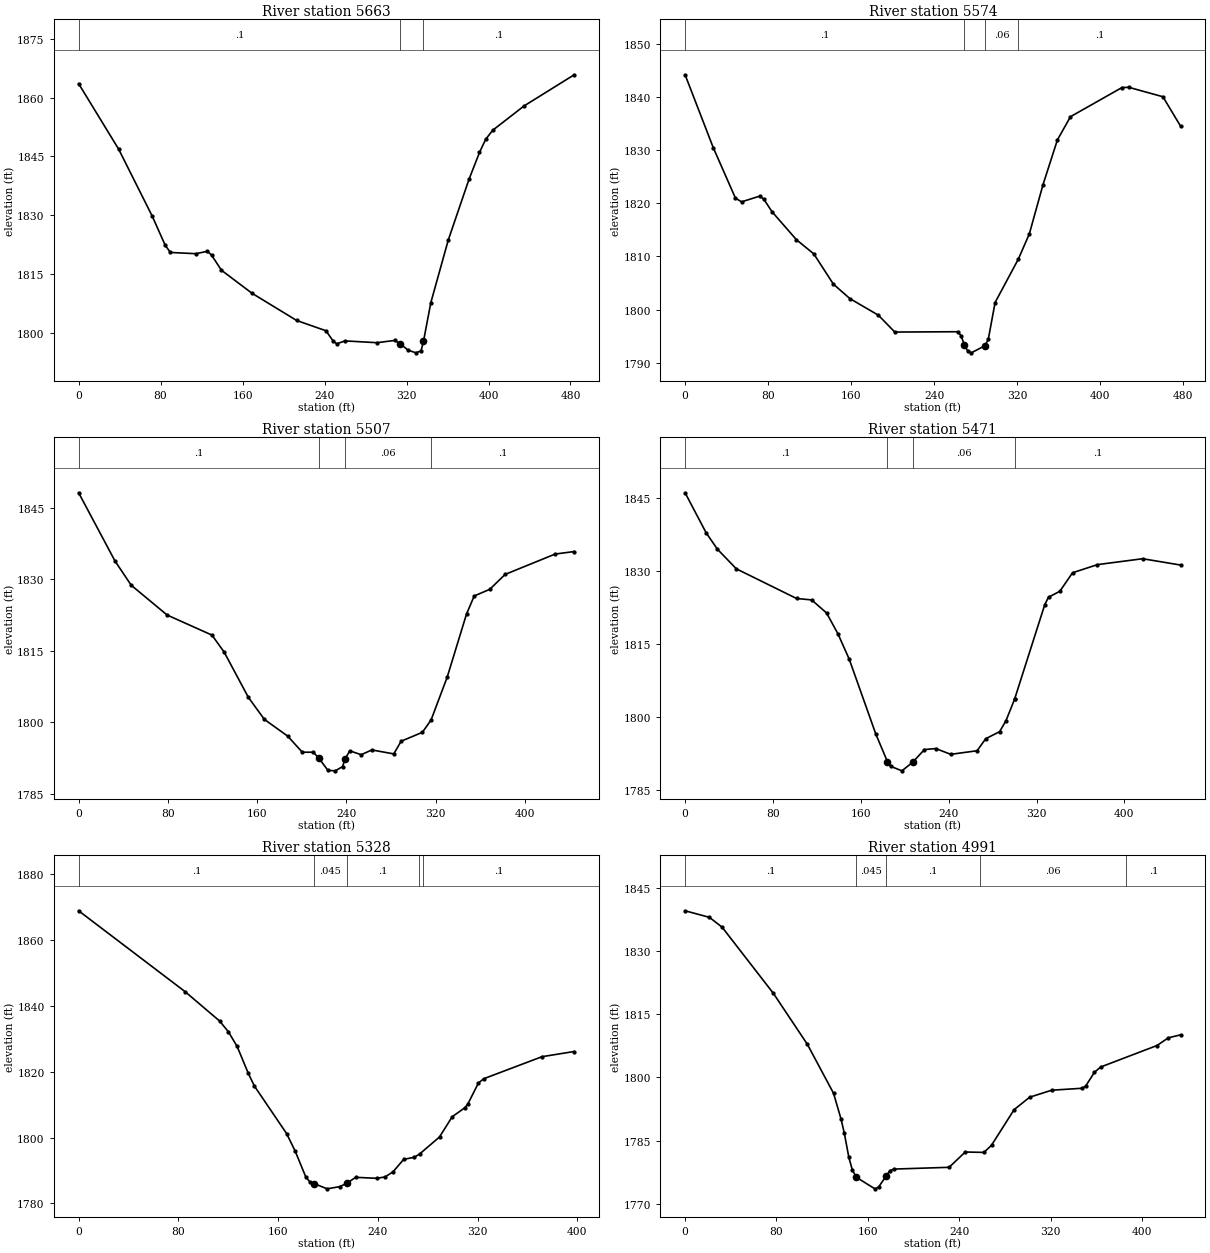
Type RM Length L Ch R = 1 ,5663    ,82.5,88.9,97
XS GIS Cut Line= 2
2067315.36112118303079.8885947912067679.94438154302762.180240706
#Sta/Elev= 30
       0 1863.57    39.1 1846.82    71.7  1829.8    84.5  1822.3    89.5 1820.46
   114.5 1820.14   125.7 1820.76   129.8 1819.75   139.4 1815.91   169.3 1810.02
   212.8 1803.08   241.4 1800.46   248.4 1797.82   251.9 1797.13     260 1797.87
   291.1 1797.41   308.5 1797.99  313.681797.171   321.6 1795.49   329.2 1794.82
   334.2 1795.35  336.551797.773   343.7 1807.63   360.7  1823.6   380.9  1839.1
   391.2 1845.99   397.2 1849.35   404.2 1851.69   434.7 1857.88   483.6 1865.84
#Mann= 3 ,-1 , 0
       0      .1       0  313.68    .045       0  336.55      .1       0
Bank Sta=313.68,336.55
XS Rating Curve= 0 ,0
Exp/Cntr=0.5,0.3

Type RM Length L Ch R = 1 ,5574    ,70,66.5,68.3
XS GIS Cut Line= 5
2067360.14579766303061.1624306972067534.29435158302944.795885451
2067575.22327439302939.9807180612067633.80781096302939.980718061
 2067800.7336138302916.707409012
#Sta/Elev= 30
       0 1844.26    27.1 1830.54    48.5 1821.02    54.4  1820.3      72 1821.38
    75.9  1820.8    83.8 1818.44   107.4 1813.15   124.1 1810.49     143 1804.78
   158.8 1802.07   186.4 1798.92   202.2 1795.75   262.8 1795.81     266 1795.09
   269.3 1793.34   272.6 1792.13   275.9 1791.83     289 1793.16   292.3 1794.35
   298.9 1801.32   321.2 1809.46   331.9 1814.25   345.1 1823.54     359 1831.99
   371.6 1836.36   421.3 1841.86   427.9 1841.89   460.7 1840.12   477.8 1834.55
#Mann= 4 ,-1 , 0
       0      .1       0   269.3    .045       0     289     .06       0
   321.2      .1       0
#XS Ineff= 2 , 0
           259.3  1795.3     299          1795.3
Permanent Ineff=
       F       F
Bank Sta=269.3,289
XS Rating Curve= 0 ,0
Exp/Cntr(USF)=0,0
Exp/Cntr=0.5,0.3

Type RM Length L Ch R = 1 ,5507    ,39.6,36.8,33.1
XS GIS Cut Line= 4
2067364.15843715303077.212988662 2067526.2690726303001.775366227
2067639.42550625303001.7753662272067783.88052794302953.623692332
#Sta/Elev= 30
       0 1848.13    32.6 1833.83    47.1 1828.76    79.3 1822.51   119.5  1818.3
   130.4 1814.76   152.1 1805.27   166.5 1800.63   187.4 1797.13   200.5 1793.75
   210.3 1793.76   215.2 1792.55   223.5 1789.94     230 1789.85   236.6 1790.74
  238.871792.384   243.1 1794.04   253.3 1793.23   262.8 1794.23   282.5  1793.4
   289.1 1796.06   308.1 1797.92   315.9 1800.49   330.4  1809.5   347.7 1822.72
   354.6  1826.5   368.5 1827.89   382.3 1831.02   427.2 1835.29   444.2 1835.81
#Mann= 4 ,-1 , 0
       0      .1       0   215.2    .045       0  238.87     .06       0
   315.9      .1       0
Bank Sta=215.2,238.87
XS Rating Curve= 0 ,0
Exp/Cntr(USF)=0,0
Exp/Cntr=0.5,0.3

Type RM Length L Ch R = 1 ,5471    ,146.6,142.7,137.7
XS GIS Cut Line= 2
2067385.16297314 303094.170692312067817.32570566302964.521872554
#Sta/Elev= 30
       0  1846.1    19.2 1837.86    29.5 1834.49    46.7 1830.47   101.5 1824.38
   115.2 1824.09   128.8 1821.41   139.1 1817.15   149.4 1811.94   173.6 1796.56
   184.2 1790.87   187.1 1789.91   197.4 1788.97   207.2 1790.73   217.9 1793.34
   228.2 1793.55   241.9 1792.36   265.9  1793.1   273.7 1795.57   286.4 1797.02
   292.2 1799.29   300.1 1803.74   300.1 1803.76   327.5 1823.13   330.9 1824.65
   341.2 1825.86   352.8 1829.67   375.5 1831.34   416.6 1832.55   451.2 1831.25
#Mann= 4 ,-1 , 0
       0      .1       0   184.2    .045       0   207.2     .06       0
   300.1      .1       0
Bank Sta=184.2,207.2
XS Rating Curve= 0 ,0
Exp/Cntr(USF)=0,0
Exp/Cntr=0.3,0.1

Type RM Length L Ch R = 1 ,5328    ,350.6,336.7,326.2
XS GIS Cut Line= 2
2067492.44442844303279.107356459 2067797.1318112303023.898877382
#Sta/Elev= 30
       0 1868.73    85.3 1844.24   113.1  1835.3   120.1 1832.05   127.1 1827.62
   136.1 1819.41     141 1815.57   166.8 1801.19   173.7 1795.84   182.1 1788.11
   185.3 1786.59  188.951786.009   199.3 1784.44   209.4 1785.11  215.011786.106
   222.2 1787.93   239.3 1787.63   245.8 1788.06   252.2 1789.63   260.7 1793.38
   269.3 1794.02   273.6 1795.05   289.4 1800.16   299.6  1806.3   309.8 1809.04
   312.1 1810.14   320.6 1816.51   324.9 1817.82   371.6  1824.5   397.4 1826.07
#Mann= 5 ,-1 , 0
       0      .1       0  188.95    .045       0  215.01      .1       0
   272.9     .06       0  275.79      .1       0
Bank Sta=188.95,215.01
XS Rating Curve= 0 ,0
Exp/Cntr=0.3,0.1

Type RM Length L Ch R = 1 ,4991    ,279.5,293.9,305.8
XS GIS Cut Line= 2
2067918.22572911303514.7843785442067880.46530595303082.492592216
#Sta/Elev= 30
       0 1839.55    21.3 1837.99    32.4 1835.66    77.3 1819.95     107 1807.88
     130 1796.22   136.6 1790.06   139.4 1786.77   143.4    1781   146.5 1777.97
  150.081776.273   166.2 1773.55   169.5    1774  175.781776.497   179.4 1777.86
   182.7 1778.24   231.2 1778.66   245.3 1782.29   261.7  1782.2   268.3  1783.9
   288.1 1792.35   301.7  1795.3     321 1796.96   347.4 1797.42   350.7 1797.92
   358.4  1801.2   363.8 1802.46   413.2 1807.57   423.1 1809.39   433.9 1810.11
#Mann= 5 ,-1 , 0
       0      .1       0  150.08    .045       0  175.78      .1       0
  257.92     .06       0   386.4      .1       0
Bank Sta=150.08,175.78
XS Rating Curve= 0 ,0
Exp/Cntr=0.3,0.1

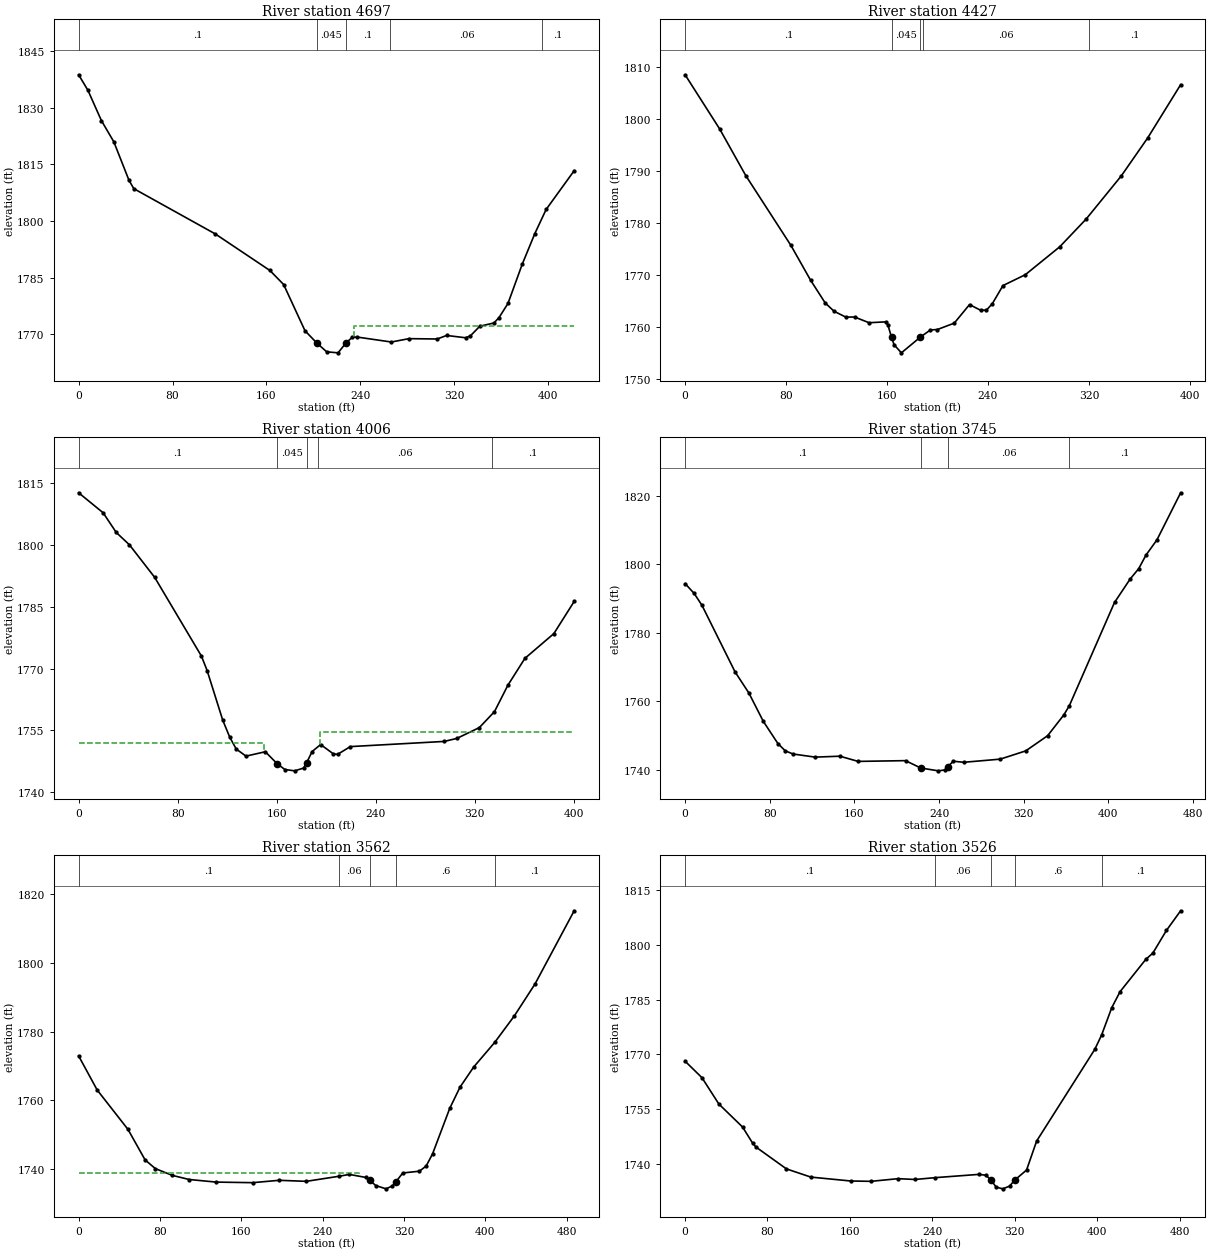
Type RM Length L Ch R = 1 ,4697    ,271.5,270.4,268.6
XS GIS Cut Line= 2
2067981.18131185303510.9205411232068325.49459961303266.493536547
#Sta/Elev= 30
       0 1838.75     7.9 1834.65    19.4 1826.61      30 1820.98    42.9 1810.79
      47 1808.57   116.5 1796.56     163 1786.88   174.7 1783.16   192.9 1770.91
  202.941767.663   211.4 1765.32   221.1 1765.05  227.721767.632   233.2 1769.17
   237.2 1769.24   266.5 1767.92   281.5 1768.81   305.6 1768.72   313.6 1769.66
   329.7 1769.05   333.8 1769.53   341.9 1772.11   353.9 1772.96   358.3 1774.41
   365.9 1778.15     378 1788.51   388.8 1796.68   398.4 1803.05   422.3 1813.33
#Mann= 5 ,-1 , 0
       0      .1       0  202.94    .045       0  227.72      .1       0
  265.62     .06       0  395.25      .1       0
#XS Ineff= 2 , 0
                          234.58         1772.06
Permanent Ineff=
       F       F
Bank Sta=202.94,227.72
XS Rating Curve= 0 ,0
Exp/Cntr=0.3,0.1

Type RM Length L Ch R = 1 ,4427    ,427.6,421.1,414.8
XS GIS Cut Line= 2
2068200.93087235303709.5175848752068492.36303228303446.288452551
#Sta/Elev= 30
       0 1808.55    27.4 1798.11    48.1 1789.12    83.9 1775.66    99.4 1768.99
     111  1764.6     118    1763   127.3 1761.87   134.3 1761.88   145.8 1760.78
     159 1760.95   160.7 1760.37  163.631757.941   165.6 1756.54   171.4 1754.98
  186.54 1758.03   194.4 1759.39   199.9 1759.47   213.3  1760.7   225.4 1764.28
   234.2 1763.18   238.8 1763.21   243.5 1764.46   251.9 1767.94   269.6 1770.03
   296.9 1775.41   317.8 1780.75   345.7 1789.08   366.6 1796.39   392.7 1806.64
#Mann= 5 ,-1 , 0
       0      .1       0  163.63    .045       0  186.54      .1       0
  188.79     .06       0  320.13      .1       0
Bank Sta=163.63,186.54
XS Rating Curve= 0 ,0
Exp/Cntr=0.3,0.1

Type RM Length L Ch R = 1 ,4006    ,260.5,260.8,260.6
XS GIS Cut Line= 2
2068536.13459828304027.8118957882068655.92635345303645.867449716
#Sta/Elev= 30
       0 1812.65    19.8  1807.8    30.4 1803.02      41 1800.04    61.4 1792.15
    99.2 1773.04   103.8 1769.53   116.4 1757.51   122.1 1753.35   127.3  1750.5
   135.2 1748.78   150.8 1749.84   160.5  1746.9   166.6 1745.53   174.5 1745.21
   181.7 1745.88   184.2 1747.18   188.6 1749.89   195.5 1751.59   205.8 1749.32
   209.2 1749.21   219.5 1751.09   295.2 1752.34   305.5 1753.07   323.7  1755.7
   335.9 1759.56   346.8    1766   360.5 1772.49   383.9  1778.5   400.3 1786.29
#Mann= 5 ,-1 , 0
       0      .1       0   160.5    .045       0   184.2      .1       0
  193.09     .06       0  333.84      .1       0
#XS Ineff= 2 , 0
          149.41 1752.06  195.25         1754.57
Permanent Ineff=
       F       F
Bank Sta=160.5,184.2
XS Rating Curve= 0 ,0
Exp/Cntr=0.3,0.1

Type RM Length L Ch R = 1 ,3745    ,185.3,182.8,177.4
XS GIS Cut Line= 2
2068756.62070584304184.0615832952068898.98196968303737.881045207
#Sta/Elev= 30
       0 1794.38     8.5 1791.52    15.9 1788.05    47.2 1768.57    60.2 1762.43
    73.9 1754.11    87.7 1747.62    94.6  1745.5     102 1744.56   122.9 1743.65
   146.3 1743.92   163.5  1742.4   208.3 1742.62  222.711740.467   239.3 1739.64
   245.6 1739.91  248.431740.895   253.4 1742.45   263.4 1742.14   297.8 1743.06
   321.9 1745.47   342.6 1749.91   357.9 1755.98   363.1 1758.67   405.8 1788.85
   420.5 1795.67   428.7 1798.75   435.5 1802.68   445.9 1807.15   468.3 1820.92
#Mann= 4 ,-1 , 0
       0      .1       0  222.71    .045       0  248.43     .06       0
   363.1      .1       0
Bank Sta=222.71,248.43
XS Rating Curve= 0 ,0
Exp/Cntr=0.5,0.3

Type RM Length L Ch R = 1 ,3562    ,35.7,36.4,37
XS GIS Cut Line= 4
2068976.52542069304318.3415381042068998.32250928 304225.41710779
2068998.32250928 303970.735335822069027.00288901303836.511158701
#Sta/Elev= 30
       0 1772.95    18.2 1763.06    48.5 1751.61    65.4 1742.72    75.5 1740.19
    92.3 1738.22   108.8 1737.03   135.3 1736.28   171.2 1736.11   197.2  1736.8
   223.9  1736.5   256.2 1737.98   266.3 1738.51   282.7 1737.62   286.2 1736.81
   292.3 1735.27   302.4 1734.32   308.7 1735.19   312.2 1736.41   318.8 1738.93
   335.2 1739.45   341.8 1740.94   348.1 1744.47     365  1757.7   375.1 1763.86
   388.5  1769.7   409.2 1776.86   428.6  1784.6   448.9 1793.86   487.4 1815.13
#Mann= 5 ,-1 , 0
       0      .1       0   256.2     .06       0   286.2    .045       0
   312.2      .6       0   409.2      .1       0
#XS Ineff= 2 , 0
           276.2    1739   322.2            1739
Permanent Ineff=
       F       F
Bank Sta=286.2,312.2
XS Rating Curve= 0 ,0
Exp/Cntr(USF)=0,0
Exp/Cntr=0.5,0.3

Type RM Length L Ch R = 1 ,3526    ,68,68.7,70.3
XS GIS Cut Line= 3
2069024.70845863304336.6969811282069035.03339533303987.943563656
2069054.53605354303857.161032104
#Sta/Elev= 30
       0 1768.09    16.4 1763.56    32.8 1756.34    55.8 1750.04    65.6  1745.6
    68.9 1744.53    98.4 1738.56   122.1 1736.31   160.8 1735.24   180.5 1735.15
   206.8 1735.88   223.2 1735.66   242.9 1736.16   285.5 1737.06   292.1  1736.8
   296.81735.566     302 1733.56   308.5 1733.09   315.1 1733.85   319.9 1735.46
   331.5 1738.24   341.3  1746.2   397.7 1771.31   404.3 1775.22   414.2 1782.75
   422.3 1787.16   447.4 1796.06   454.1 1797.72   467.3 1803.95   481.1 1809.34
#Mann= 5 ,-1 , 0
       0      .1       0   242.9     .06       0   296.8    .045       0
   319.9      .6       0   404.3      .1       0
Bank Sta=296.8,319.9
XS Rating Curve= 0 ,0
Exp/Cntr(USF)=0,0
Exp/Cntr=0.5,0.3