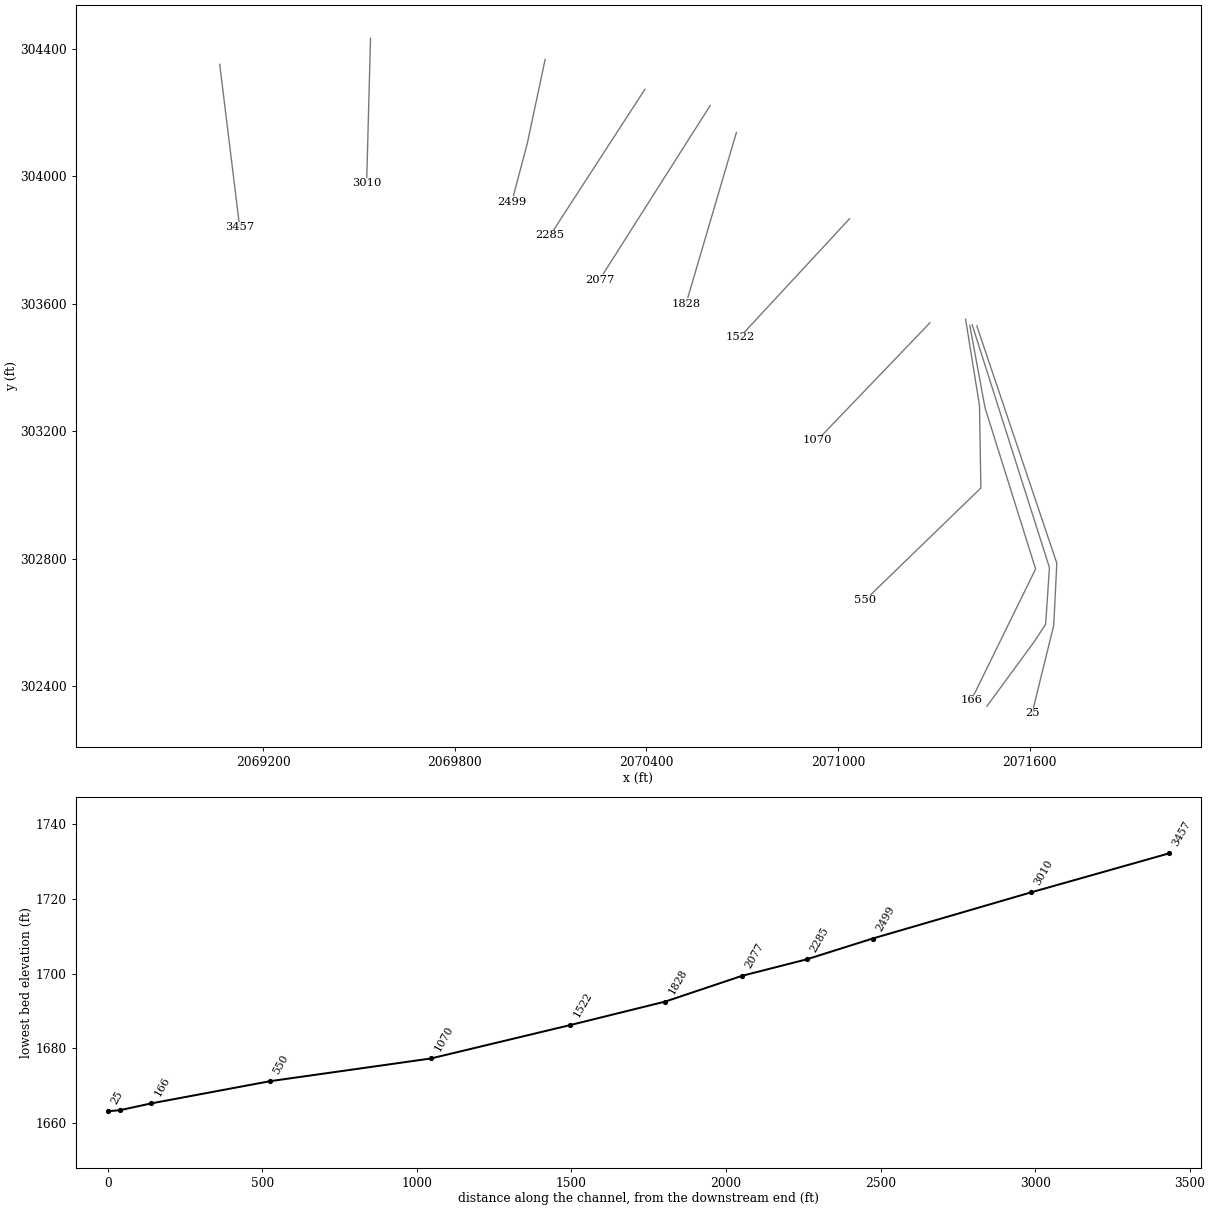
HEC-RAS study KTCHNCKT1.prj: KTCHNCKT1

--- KTCHNCKT1.g01 (geometry) --- (continued)

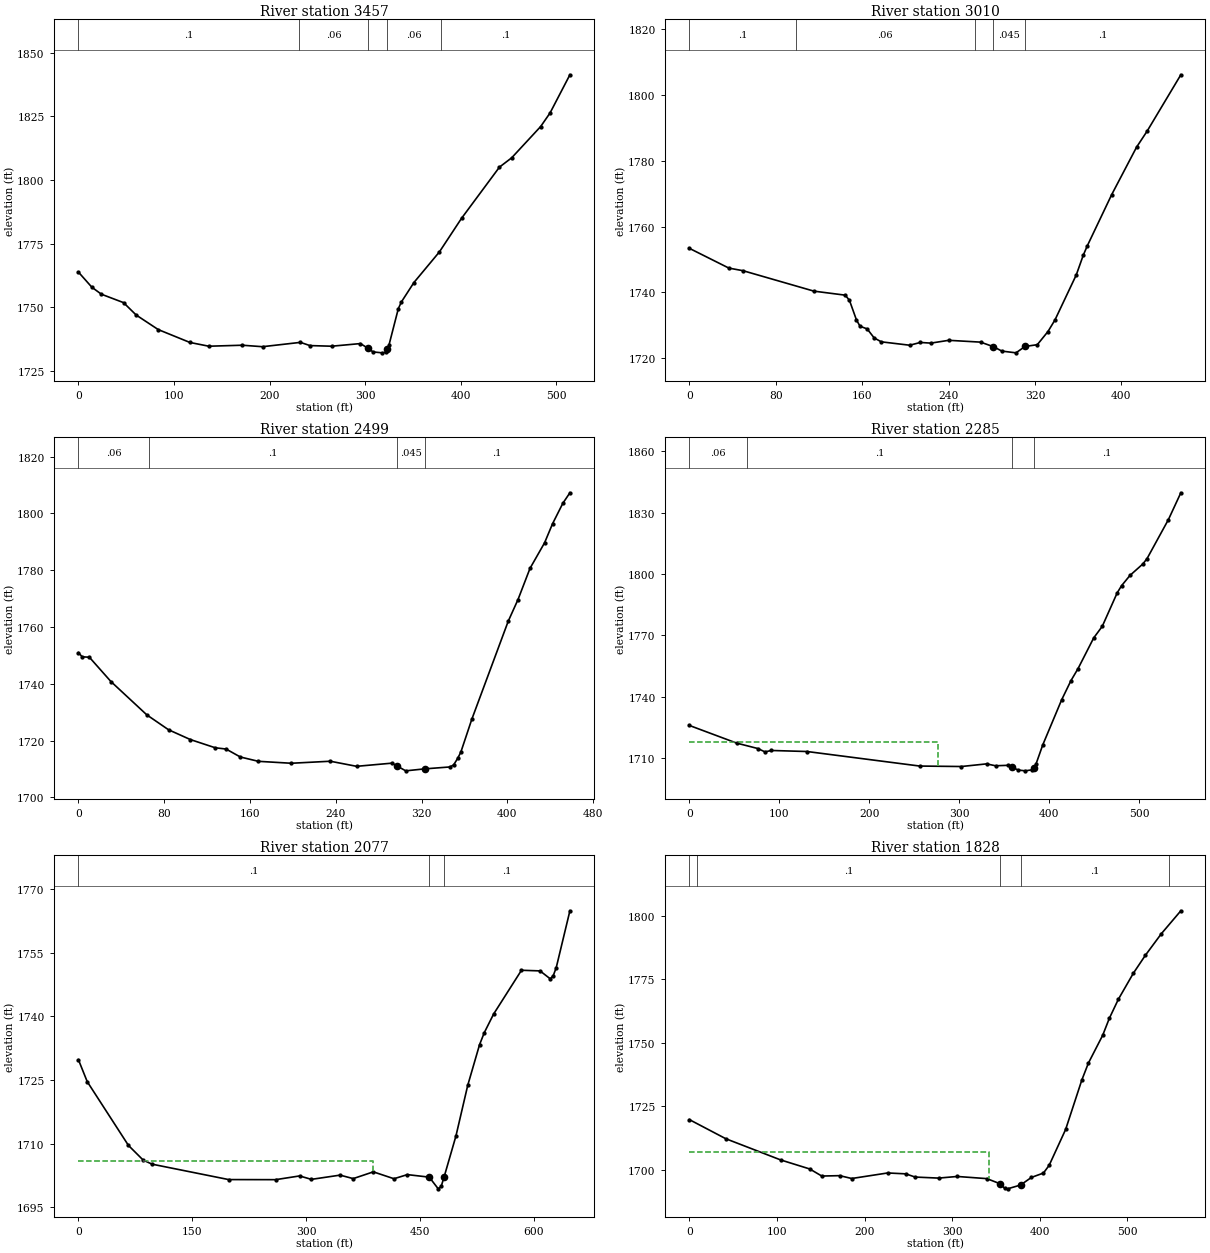
Type RM Length L Ch R = 1 ,3457    ,450.6,446.9,445
XS GIS Cut Line= 2
 2069063.9124141304350.7282447072069126.41261718303840.311614633
#Sta/Elev= 30
       0 1763.81    14.1 1757.85      24 1755.13    47.2 1751.82    60.4 1746.96
    83.5 1741.24   116.6 1736.19   136.4 1734.71   171.4  1735.1   192.6 1734.52
   232.3 1736.22   242.2 1734.96   264.9 1734.71   295.1 1735.75  303.181733.824
   308.3 1732.47   317.7 1732.11   321.5 1732.29  323.181733.594   324.8    1735
   334.7 1749.48     338 1752.15     351 1759.71   377.7 1771.75   400.8 1784.91
   440.5 1805.02   453.3 1808.68   483.6 1820.95   493.4 1826.26   514.2 1841.27
#Mann= 5 ,-1 , 0
       0      .1       0  231.19     .06       0  303.18    .045       0
  323.18     .06       0  379.63      .1       0
Bank Sta=303.18,323.18
XS Rating Curve= 0 ,0
Exp/Cntr=0.3,0.1

Type RM Length L Ch R = 1 ,3010    ,513.7,510.9,507.2
XS GIS Cut Line= 2
2069536.13456678304432.3255224672069523.98203203303977.464555547
#Sta/Elev= 30
       0 1753.38    36.6 1747.38    49.7 1746.59   115.3 1740.39   144.3 1739.17
   148.2 1737.61   154.7 1731.64     158 1729.74   164.6 1728.93   171.1 1726.19
   177.7 1725.01     204 1723.98   213.8 1724.82   223.6 1724.62   240.1 1725.47
   269.6 1724.92  281.521723.535   289.3  1722.2   302.4 1721.67  310.731723.607
   322.1 1724.14     332 1728.14   338.5 1731.67   358.2 1745.32   364.7 1751.32
   368.3 1754.07     391 1769.69     414 1784.07   423.9    1789     455 1806.04
#Mann= 5 ,-1 , 0
       0      .1       0   98.41     .06       0  264.21      .1       0
  281.52    .045       0  310.73      .1       0
Bank Sta=281.52,310.73
XS Rating Curve= 0 ,0
Exp/Cntr=0.3,0.1

Type RM Length L Ch R = 1 ,2499    ,216,214.1,207
XS GIS Cut Line= 3
2070083.00978535304366.3535415382070027.45412219304104.200522542
2069978.84299895303920.173003465
#Sta/Elev= 30
       0 1750.97     3.5 1749.51    10.2 1749.36    30.3  1740.8    63.8 1729.06
      84 1723.83   104.4 1720.37   127.6 1717.48   137.7 1717.03     151 1714.23
   167.8 1712.71   198.5 1712.03   234.9 1712.74   259.4 1710.95   292.2 1712.06
   297.2 1711.06   305.2 1709.36  322.821710.052   346.5 1710.73   349.9 1711.46
   353.6 1713.72   356.6 1715.95   366.8 1727.49   400.8 1762.05   409.9 1769.66
   421.1 1780.65   434.7 1789.66   442.1 1796.34   451.7 1803.55   458.3 1807.26
#Mann= 4 ,-1 , 0
       0     .06       0   66.08      .1       0   297.2    .045       0
  322.82      .1       0
Bank Sta=297.2,322.82
XS Rating Curve= 0 ,0
Exp/Cntr=0.3,0.1

Type RM Length L Ch R = 1 ,2285    ,207.5,208.5,207
XS GIS Cut Line= 2
2070395.50981653304272.6034009612070098.63475412303814.270000041
#Sta/Elev= 30
       0 1725.96    52.6 1717.32    76.1 1714.68      84 1713.04    91.1 1713.73
   130.8 1713.22   255.9 1706.12   302.2 1705.89   330.2 1707.18   340.2 1706.26
   353.6 1706.47  358.951705.491   365.3 1704.18   373.2 1703.78     381 1704.29
  382.58 1705.08   385.3 1707.26   392.7 1716.49   413.7 1738.52     424 1747.85
   431.8 1753.67   449.3 1768.74   458.8  1774.4   475.4 1790.76   480.2 1794.22
   489.6 1799.27   503.9 1804.86   508.6 1807.52   532.3 1826.55   546.1 1839.64
#Mann= 4 ,-1 , 0
       0     .06       0   64.01      .1       0  358.95    .045       0
  382.58      .1       0
#XS Ineff= 2 , 0
          275.72 1717.76
Permanent Ineff=
       F       F
Bank Sta=358.95,382.58
XS Rating Curve= 0 ,0
Exp/Cntr=0.3,0.1

Type RM Length L Ch R = 1 ,2077    ,244.3,248.9,249.2
XS GIS Cut Line= 2
2070599.99994918304221.7939363262070253.31069112303675.211772712
#Sta/Elev= 30
       0  1729.8    11.6 1724.63    65.9 1709.61    85.4 1706.14      97  1705.2
   197.9 1701.57   259.7 1701.55   291.3 1702.43   306.8 1701.62   344.6 1702.62
   361.9  1701.8   388.4 1703.39   415.6 1701.77   433.2 1702.74   461.8 1702.15
   462.2 1702.11   473.9 1699.39   477.8 1699.98   481.7 1702.24   497.2 1711.83
   512.7 1723.74   528.3 1733.34   534.5 1736.16   546.8 1740.55   583.5 1750.87
     608 1750.72   621.5 1748.84   625.4 1749.61   629.3 1751.49   647.3 1764.88
#Mann= 3 ,-1 , 0
       0      .1       0   461.8    .045       0   481.7      .1       0
#XS Ineff= 2 , 0
          388.48 1705.89
Permanent Ineff=
       F       F
Bank Sta=462.2,481.7
XS Rating Curve= 0 ,0
Exp/Cntr(USF)=0,0
Exp/Cntr=0.3,0.1

Type RM Length L Ch R = 1 ,1828    ,312.4,306.1,297.9
XS GIS Cut Line= 2
2070681.96790501304137.1866770392070523.98200053 303598.99221538
#Sta/Elev= 30
       0 1719.75    41.7  1712.2   104.2 1703.87   137.4 1700.31   151.1 1697.53
   171.6 1697.68   185.3 1696.56   226.3 1698.74     247 1698.39   257.6 1697.13
   284.4 1696.72   305.7 1697.36   339.5 1696.51  354.251694.542   359.7 1692.75
   363.1 1692.49  377.911693.982   390.4 1696.99   404.1 1698.71   410.6 1701.74
   429.4 1715.86   447.9 1735.34   455.4    1742   471.7 1752.94   479.3 1759.63
   489.6 1767.13   506.7 1777.38   520.4 1784.43   538.7 1792.96   560.9 1801.97
#Mann= 5 ,-1 , 0
       0     .06       0    9.26      .1       0  354.25    .045       0
  377.91      .1       0  547.42      .1       0
#XS Ineff= 2 , 0
          341.94 1707.09
Permanent Ineff=
       F       F
Bank Sta=354.25,377.91
XS Rating Curve= 0 ,0
Exp/Cntr=0.3,0.1

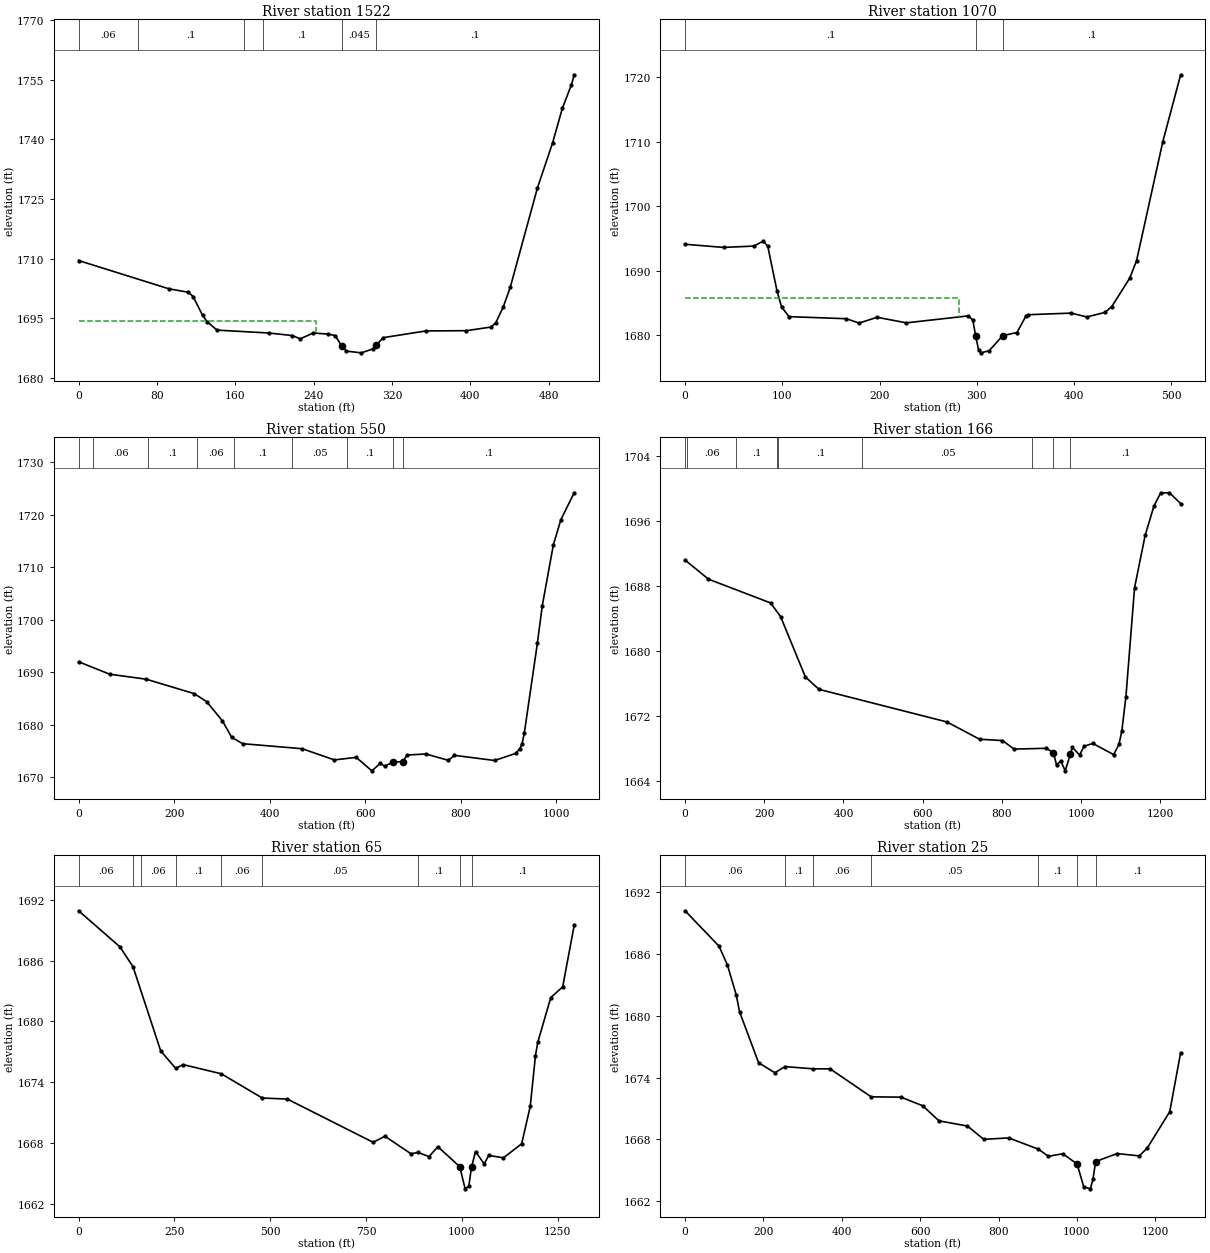
Type RM Length L Ch R = 1 ,1522    ,451.8,451.4,448.6
XS GIS Cut Line= 2
2071036.13484761303866.3535572892070692.38487893303494.825757042
#Sta/Elev= 30
       0 1709.49    92.2 1702.37   112.1  1701.5   116.9 1700.43   126.6  1695.7
   131.4 1694.04   141.4 1691.96   194.2 1691.24   218.4 1690.59   226.3 1689.77
   239.7 1691.24     255 1690.95     262 1690.59   268.9 1687.93   273.6 1686.67
   288.9 1686.24   300.5 1687.23   303.71688.099   311.3 1690.07   354.8 1691.76
   396.2 1691.82   421.3 1692.74   426.1  1693.8   433.8 1697.84   440.9 1702.74
   468.6 1727.72   484.1 1739.09   494.1 1747.81   503.4 1753.76   506.2 1756.28
#Mann= 6 ,-1 , 0
       0     .06       0   60.76      .1       0  169.05     .06       0
  188.01      .1       0   268.9    .045       0   303.7      .1       0
#XS Ineff= 2 , 0
          242.78 1694.17
Permanent Ineff=
       F       F
Bank Sta=268.9,303.7
XS Rating Curve= 0 ,0
Exp/Cntr=0.3,0.1

Type RM Length L Ch R = 1 ,1070    ,513.2,520.2,514.4
XS GIS Cut Line= 2
 2071287.8708927303539.964446291 2070935.4401671303171.909080043
#Sta/Elev= 30
       0 1694.12    39.6 1693.63    70.8 1693.84    80.3 1694.61      85 1693.83
    94.5  1686.9    99.3 1684.38   106.9  1682.9   165.7 1682.58   178.9  1681.9
   197.4  1682.8   227.6 1681.94   291.4 1683.02   295.9 1682.36  298.891679.834
   301.8 1677.74   304.2 1677.29   312.7 1677.62  326.651679.956   341.3 1680.44
   350.6 1683.02   352.9  1683.2     397 1683.45   413.2 1682.85   431.8 1683.56
   438.8 1684.47   457.3 1688.88   464.3  1691.6   491.3 1710.04   509.6 1720.39
#Mann= 3 ,-1 , 0
       0      .1       0  298.89    .045       0  326.65      .1       0
#XS Ineff= 2 , 0
          281.83 1685.75
Permanent Ineff=
       F       F
Bank Sta=298.89,326.65
XS Rating Curve= 0 ,0
Exp/Cntr=0.3,0.1

Type RM Length L Ch R = 1 ,550     ,369.8,383.8,389.1
XS GIS Cut Line= 4
2071399.78143004303551.3863394562071443.18423036303280.118837371
2071447.52444476 303021.872306632071085.11145568 302670.31001763
#Sta/Elev= 30
       0 1691.98    65.2 1689.61   141.7 1688.66   242.3 1685.91   267.9  1684.4
   300.8 1680.79   320.5 1677.61   343.5 1676.39   468.2 1675.43   535.7  1673.3
   581.4 1673.78   614.2 1671.22   631.7 1672.64   640.8 1672.12   659.1 1672.89
   678.8 1672.98   688.1 1674.23   727.3 1674.43   774.4 1673.22   787.1 1674.17
   871.3 1673.19   915.4 1674.54   924.2 1675.44   928.8 1676.39   933.4 1678.37
   960.8 1695.48   971.1 1702.66   994.3 1714.23    1010 1719.02  1037.9 1724.15
#Mann= 9 ,-1 , 0
       0    .055       0   30.36     .06       0  145.88      .1       0
  248.38     .06       0  325.46      .1       0  447.22     .05       0
   561.5      .1       0   659.1    .045       0   678.8      .1       0
Bank Sta=659.1,678.8
XS Rating Curve= 0 ,0
Exp/Cntr=0.3,0.1

Type RM Length L Ch R = 1 ,166     ,105.4,101.3,99.7
XS GIS Cut Line= 4
2071412.80240136303531.8552105432071460.54541612303273.608679801
2071618.96537486302767.9663183842071417.14261577 302355.63971521
#Sta/Elev= 30
       0 1691.17      59 1688.83   215.9 1685.91   241.2 1684.23   303.8 1676.82
   338.1  1675.3   661.6 1671.29   743.8 1669.17   801.6 1669.01     831 1667.96
   912.5 1668.06  930.221667.519   938.1 1666.03     949  1666.5     960 1665.29
  973.091667.325   978.2 1668.16   996.5 1667.23  1007.5  1668.3  1029.6 1668.66
  1082.4 1667.28  1095.8 1668.53  1103.2 1670.23  1113.4 1674.41  1135.3  1687.8
  1162.1 1694.24  1184.1  1697.8    1201 1699.42  1223.4 1699.44  1251.6 1698.12
#Mann= 9 ,-1 , 0
       0    .055       0    4.58     .06       0  128.74      .1       0
  232.09     .06       0  235.28      .1       0  447.96     .05       0
  877.38      .1       0  930.22    .045       0  973.09      .1       0
Bank Sta=930.22,973.09
XS Rating Curve= 0 ,0
Exp/Cntr=0.3,0.1

Type RM Length L Ch R = 1 ,65      ,31.6,40,45.8
XS GIS Cut Line= 5
2071420.40065135303533.6688814252071662.27894895302772.288427409
2071650.36376187302594.7521400092071614.61820065 302539.94227947
2071466.43528845302337.468293287
#Sta/Elev= 30
       0 1690.91   107.5 1687.36   141.9 1685.39   214.2 1677.08   253.2 1675.36
   272.8 1675.73   372.6 1674.82   479.3 1672.43   544.7 1672.33   768.5 1668.06
   799.3 1668.66   867.3 1666.93   885.8 1667.06   914.5 1666.65   937.5 1667.63
   994.5 1665.66  1008.7 1663.47  1018.2 1663.74  1025.3 1665.62  1035.8 1667.15
  1058.4 1665.93  1070.1 1666.77  1108.7 1666.53  1156.2 1667.92  1178.5  1671.6
  1192.2 1676.62  1198.1 1677.92  1232.1 1682.34  1263.2  1683.4  1293.2 1689.46
#Mann= 9 ,-1 , 0
       0     .06       0   141.9      .1       0   162.6     .06       0
   253.2      .1       0   372.6     .06       0   479.3     .05       0
   885.8      .1       0   994.5    .045       0  1025.3      .1       0
Bank Sta=994.5,1025.3
XS Rating Curve= 0 ,0
Exp/Cntr(USF)=0,0
Exp/Cntr=0.3,0.1

Type RM Length L Ch R = 1 ,25      ,25,25,25
XS GIS Cut Line= 4
2071434.91806311303530.2122594182071685.35015327302786.071191532
2071675.80988317302591.688188222 2071607.8354587 302315.02035529
#Sta/Elev= 30
       0 1690.21    86.6 1686.77   107.9 1684.95   130.6 1682.03   139.1 1680.38
   187.5 1675.45     229 1674.47   254.9 1675.07   327.5 1674.85   370.1 1674.85
   474.9 1672.13     551  1672.1   606.4 1671.26   647.9  1669.8   720.6 1669.29
   762.2    1668   825.8 1668.14   901.3 1667.05   927.4 1666.35   963.7  1666.6
  1000.4 1665.61  1017.3  1663.4  1034.2 1663.19    1041 1664.11  1047.7 1665.84
  1102.6 1666.62  1159.2 1666.39  1179.5 1667.15  1236.9 1670.69  1264.7 1676.42
#Mann= 7 ,-1 , 0
       0     .06       0   254.9      .1       0   327.5     .06       0
   474.9     .05       0   901.3      .1       0  1000.4    .045       0
  1047.7      .1       0
Bank Sta=1000.4,1047.7
XS Rating Curve= 0 ,0
Exp/Cntr(USF)=0,0
Exp/Cntr=0.3,0.1
LCMann Table=0

Chan Stop Cuts=-1
Use User Specified Reach Order=0
Composite Channel Slope=5